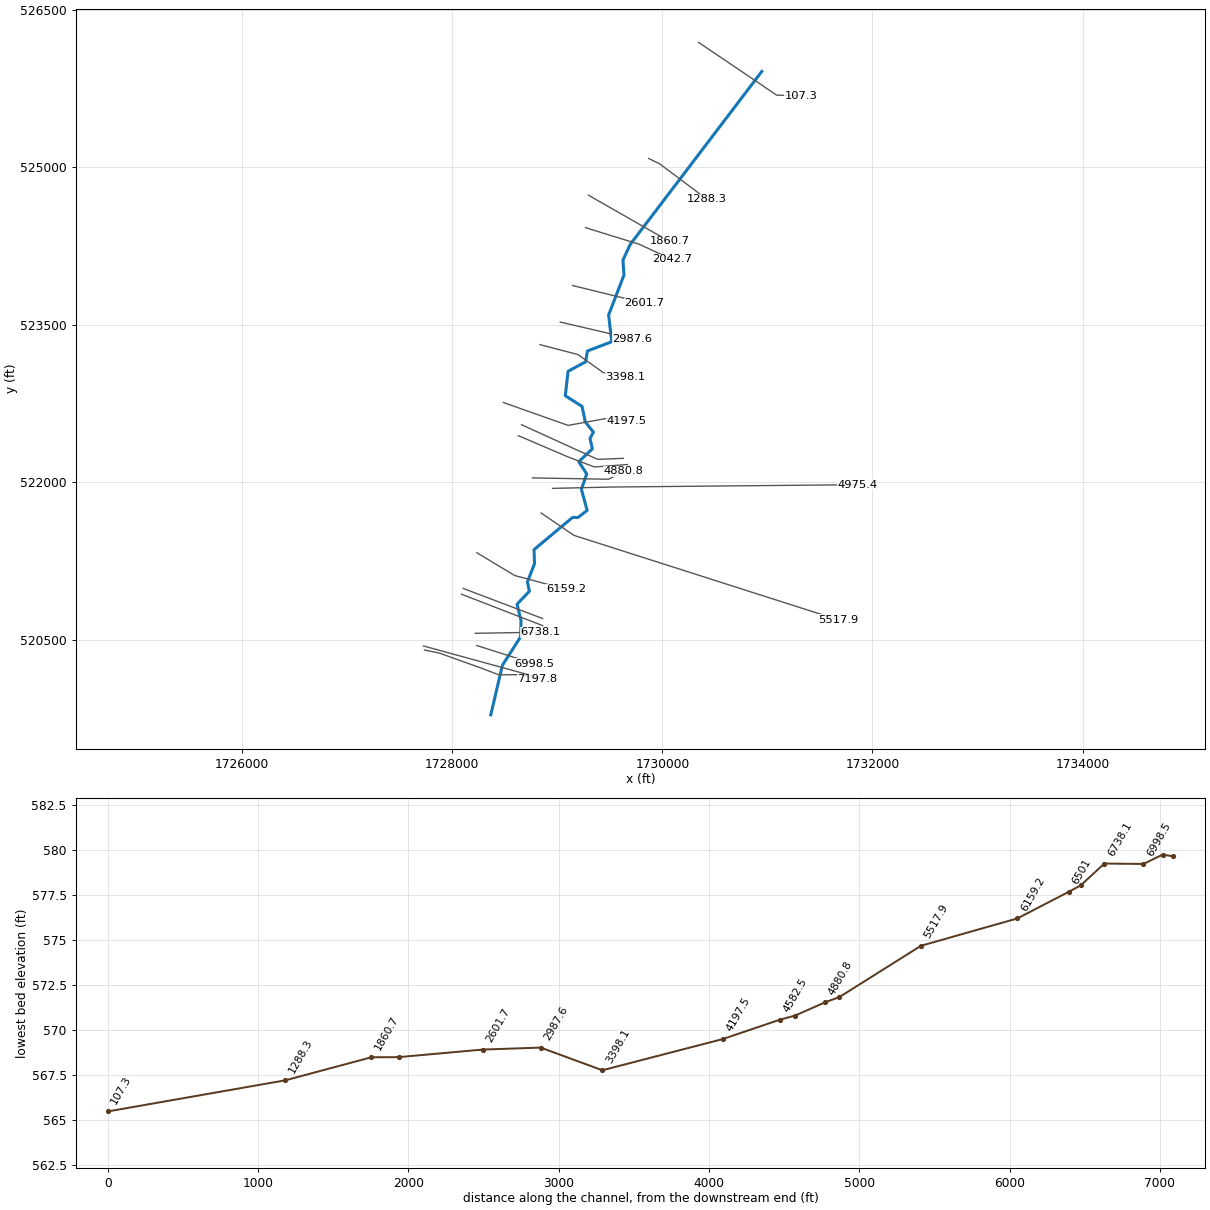
--- ArmourCr.prj (project) ---

Proj Title=ArmourCr
Current Plan=p01
Default Exp/Contr=0,0
English Units
Geom File=g01
Flow File=f01
Plan File=p01
BEGIN DESCRIPTION:
AMEC Environment & Infrastructure, 2013
Projection: NAD 1983 State Plane West Virginia South FIPS 4702 (US Feet)
Vertical Datum: NAVD 1988
END DESCRIPTION:
DSS Export Rating Curves= 0
DSS Export Rating Curve Sorted= 0
DSS Export Volume Flow Curves= 0
DXF OffsetX= 0
DXF OffsetY= 0
DXF ScaleX= 0
DXF ScaleY= 0

--- ArmourCr.p01 (plan) ---

Plan Title=Floodplain
Program Version=4.00
Geom File=g01
Flow File=f01
K Sum by GR=0
Std Step Tol=0.01
Critical Tol=0.01
Num of Std Step Trials=20
Max Error Tol=0.3
Flow Tol Ratio=0.001
Split Flow NTrial=30
Split Flow Tol=0.02
Split Flow Ratio=0.02
Log Output Level=0
Friction Slope Method=1
Unsteady Friction Slope Method=2
Unsteady Bridges Friction Slope Method=1
Global Log Level=0
CheckData=False
Run HTab=0
Run UNet=0
Run PostProcess=0
UNET Theta=0
UNET Theta Warmup=0
UNET ZTol=0
UNET ZSATol=0
UNET MxIter=0
UNET MaxInSteps=0
UNET DtIC=0
UNET DtMin=0
UNET MaxCRTS=0
UNET WFStab=0
UNET SFStab=0
UNET WFX=0
UNET SFX=0
UNET DSS MLevel=0
UNET DZMax Abort=0
UNET Convert EG Bridges=0
UNET Use Existing IB Tables=0
UNET Froude Limit=0
UNET Froude Power=0
Write IC File=0
Echo Input=False
Echo Output=False
Write Detailed=0

--- ArmourCr.f01 (steady flow) ---

Flow Title=USGS Regress. Eqn. (2010) - Western-Plateaus
Program Version=4.10
Number of Profiles= 1
Profile Names=P100yr
River Rch & RM=ArmourCr,Main            ,7197.8
    1098
River Rch & RM=ArmourCr,Main            ,6159.2
    1150
River Rch & RM=ArmourCr,Main            ,5517.9
    1174
River Rch & RM=ArmourCr,Main            ,4975.4
    1774
River Rch & RM=ArmourCr,Main            ,4880.8
    1775
River Rch & RM=ArmourCr,Main            ,2042.7
    1804
River Rch & RM=ArmourCr,Main            ,1860.7
    1808
River Rch & RM=ArmourCr,Main            ,107.3
    1839
Boundary for River Rch & Prof#=ArmourCr,Main            , 1
Up Type= 0
Dn Type= 3
Dn Slope=0.0015
DSS Import GetInterval= 0
DSS Import GetPeak= 0
DSS Import FillOption= 0

--- ArmourCr.g01 (geometry) ---

Geom Title=USGS 3m DEM
Program Version=4.10

River Reach=ArmourCr        ,Main
Reach XY= 30
     1728366.725      519787.834     1728477.243      520259.618
     1728650.386      520530.027     1728654.887      520685.619
     1728616.909      520840.784     1728734.097      520964.482
     1728715.651      521053.458     1728782.925      521225.984
     1728778.585      521360.532     1729146.423      521667.607
     1729196.779      521666.225     1729284.019      521733.934
     1729229.331      521934.454     1729280.112      522080.288
     1729204.592      522197.475     1729333.498      522319.871
     1729311.362      522418.829     1729343.914      522478.725
     1729267.092      522573.777     1729235.592      522723.615
      1729076.19      522825.241     1729102.227      523057.596
     1729269.696      523147.996     1729286.623      523250.861
     1729518.394      523339.402     1729488.446      523593.309
     1729634.279      523972.215     1729625.164      524116.746
     1729694.175      524265.184     1730946.223      525911.022

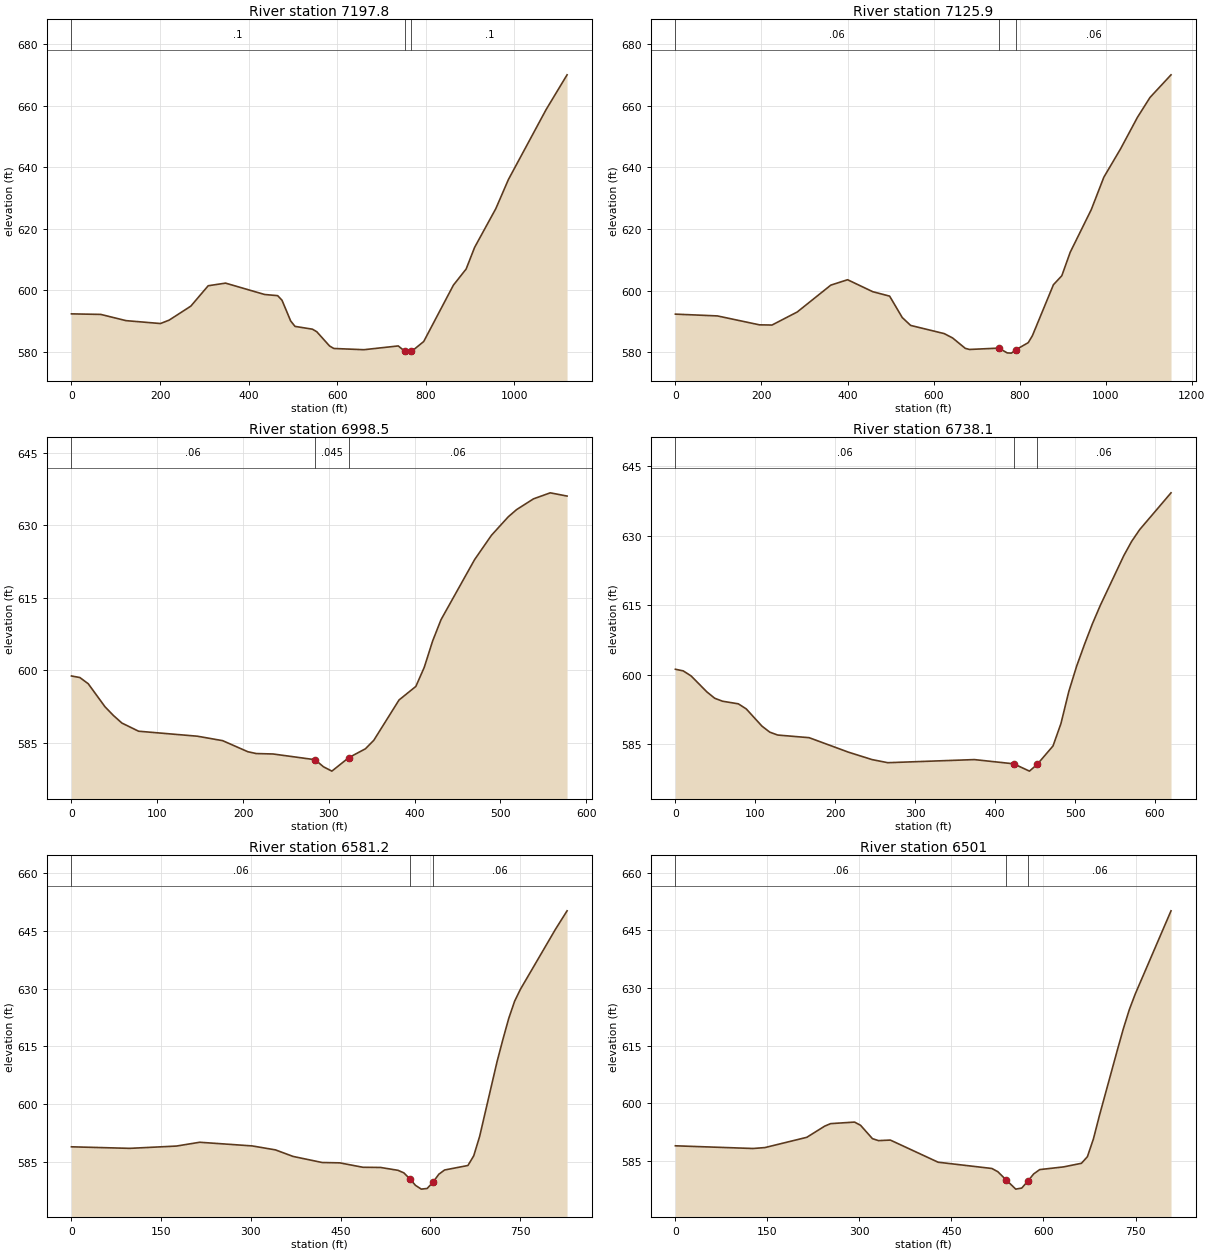
Type RM Length L Ch R = 1 ,7197.8  ,74.5,71.9,65.4
XS GIS Cut Line= 6
     1727735.743      520405.147     1727874.999      520376.784
     1728262.448      520237.979     1728443.461      520169.114
     1728654.103      520170.723     1728808.866      520126.971
#Sta/Elev= 30
       0  592.38    66.3   592.2   123.2  590.18   200.9  589.24   220.5  590.34
   269.5  594.89   308.7  601.51   347.9  602.36   436.1  598.67   465.5  598.29
   475.3  596.81   494.9  590.07   504.7  588.31   543.9  587.41   553.7  586.59
   582.7  581.94   592.4  581.14   660.2  580.74   737.7  581.97   752.5  580.24
   756.9  579.63   767.5  580.16   795.2   583.4   862.2   601.7     891  606.95
   910.1  613.97     958  626.56   986.4     636  1071.5  658.72  1118.8     670
#Mann= 3 , 0 , 0
       0      .1       0   752.5    .045       0   767.5      .1       0
Bank Sta=752.5,767.5
XS Rating Curve= 0 ,0
Exp/Cntr=0.3,0.1

Type RM Length L Ch R = 1 ,7125.9  ,128.3,127.4,126.5
XS GIS Cut Line= 2
     1727726.278      520443.718     1728837.255      520139.251
#Sta/Elev= 30
       0  592.38    97.6   591.8   195.2  588.91   224.5  588.84   283.1  593.07
   361.2  601.79   400.2  603.54   458.8  599.65   497.9  598.22   527.2  591.28
   546.7  588.72   624.8  586.06   644.3  584.65   673.6  581.29   683.4  580.92
   751.7  581.35   771.2   579.8     781  579.73   790.7  580.78     820  583.12
   829.8  585.41   878.6  601.92   898.1  604.84   917.6  612.45   966.5  626.27
   995.8  636.81  1034.8  646.04  1073.8  656.21  1103.1  662.68  1151.9  670.01
#Mann= 3 , 0 , 0
       0     .06       0   751.7    .045       0   790.7     .06       0
Bank Sta=751.7,790.7
XS Rating Curve= 0 ,0
Exp/Cntr=0.3,0.1

Type RM Length L Ch R = 1 ,6998.5  ,252.9,260.4,267.6
XS GIS Cut Line= 2
     1728234.299      520447.903     1728784.803      520272.535
#Sta/Elev= 30
       0  598.86     9.8  598.54    19.6  597.25    39.2  592.48      49  590.69
    58.8  589.14    78.3  587.45   146.9  586.42   176.3   585.5   205.6  583.22
   215.4  582.84     235  582.75     284  581.57   293.8  580.11   303.6  579.21
   323.2  581.98   342.7  583.82   352.5  585.58   381.9   593.9   401.5   596.7
   411.3  600.64   421.1   606.1   430.9   610.5     470  622.89   489.6   627.9
   509.2  631.72     519  633.22   538.6  635.43   558.2  636.68   577.8  636.01
#Mann= 3 , 0 , 0
       0     .06       0     284    .045       0   323.2     .06       0
Bank Sta=284,323.2
XS Rating Curve= 0 ,0
Exp/Cntr=0.3,0.1

Type RM Length L Ch R = 1 ,6738.1  ,171.1,156.9,139.7
XS GIS Cut Line= 2
     1728218.664      520564.253     1728838.622      520574.703
#Sta/Elev= 30
       0  601.22     9.8  600.87    19.7  599.77    39.4  596.33    49.2  594.96
      59  594.32    78.7  593.76    88.6  592.67   108.3  588.94   118.1  587.64
     128  587.02   167.3  586.45   216.5  583.32     246  581.72   265.7  581.05
     374  581.72   423.2  580.81   442.9  579.23   452.7   580.7   472.4  584.67
   482.3   589.5   492.1   596.4   501.9  601.88   511.8  606.61   521.6  611.01
   531.5     615     561  625.78   570.8  628.84   580.7  631.35     620  639.31
#Mann= 3 , 0 , 0
       0     .06       0   423.2    .045       0   452.7     .06       0
Bank Sta=423.2,452.7
XS Rating Curve= 0 ,0
Exp/Cntr=0.3,0.1

Type RM Length L Ch R = 1 ,6581.2  ,75.5,80.1,87.8
XS GIS Cut Line= 2
     1728088.402      520935.874     1728861.194      520637.221
#Sta/Elev= 30
       0  588.99    97.5  588.59   175.4  589.18   214.4  590.17   302.2  589.22
   341.1  588.19   370.4   586.5   419.1  584.92   448.4  584.83   487.4  583.68
   516.6  583.64   545.8   582.9   555.6  582.24   565.3  580.75   575.1     579
   584.8  578.02   594.6  578.19   604.3  579.79   614.1  581.88   623.8  582.98
   662.8  584.15   672.5  586.67   682.3  591.66   711.5  611.09   721.3  616.86
     731  622.28   740.8  626.72   750.5  629.82     809  645.35   828.5  650.16
#Mann= 3 , 0 , 0
       0     .06       0   565.3    .045       0   604.3     .06       0
Bank Sta=565.3,604.3
XS Rating Curve= 0 ,0
Exp/Cntr=0.3,0.1

Type RM Length L Ch R = 1 ,6501    ,338.7,341.8,343.7
XS GIS Cut Line= 2
     1728104.029      520991.445     1728859.454      520704.947
#Sta/Elev= 30
       0  588.93   126.5  588.23     146  588.47   214.2  591.14   243.4  594.05
   253.1   594.7     292   595.1   301.8  594.27   321.2  590.79     331  590.28
   350.4  590.42   428.3  584.66   515.9  583.03   525.6  582.19   538.9   580.1
   554.8  577.66   564.6  577.94   574.3   579.7     584  581.61   593.8  582.74
   632.7  583.44   661.9  584.38   671.6   586.1   681.4  590.72   691.1  596.75
   720.3  613.77   730.1  619.34   739.8   624.3   749.5  628.39   807.9  650.06
#Mann= 3 , 0 , 0
       0     .06       0   538.9    .045       0   574.3     .06       0
Bank Sta=538.9,574.3
XS Rating Curve= 0 ,0
Exp/Cntr=0.3,0.1

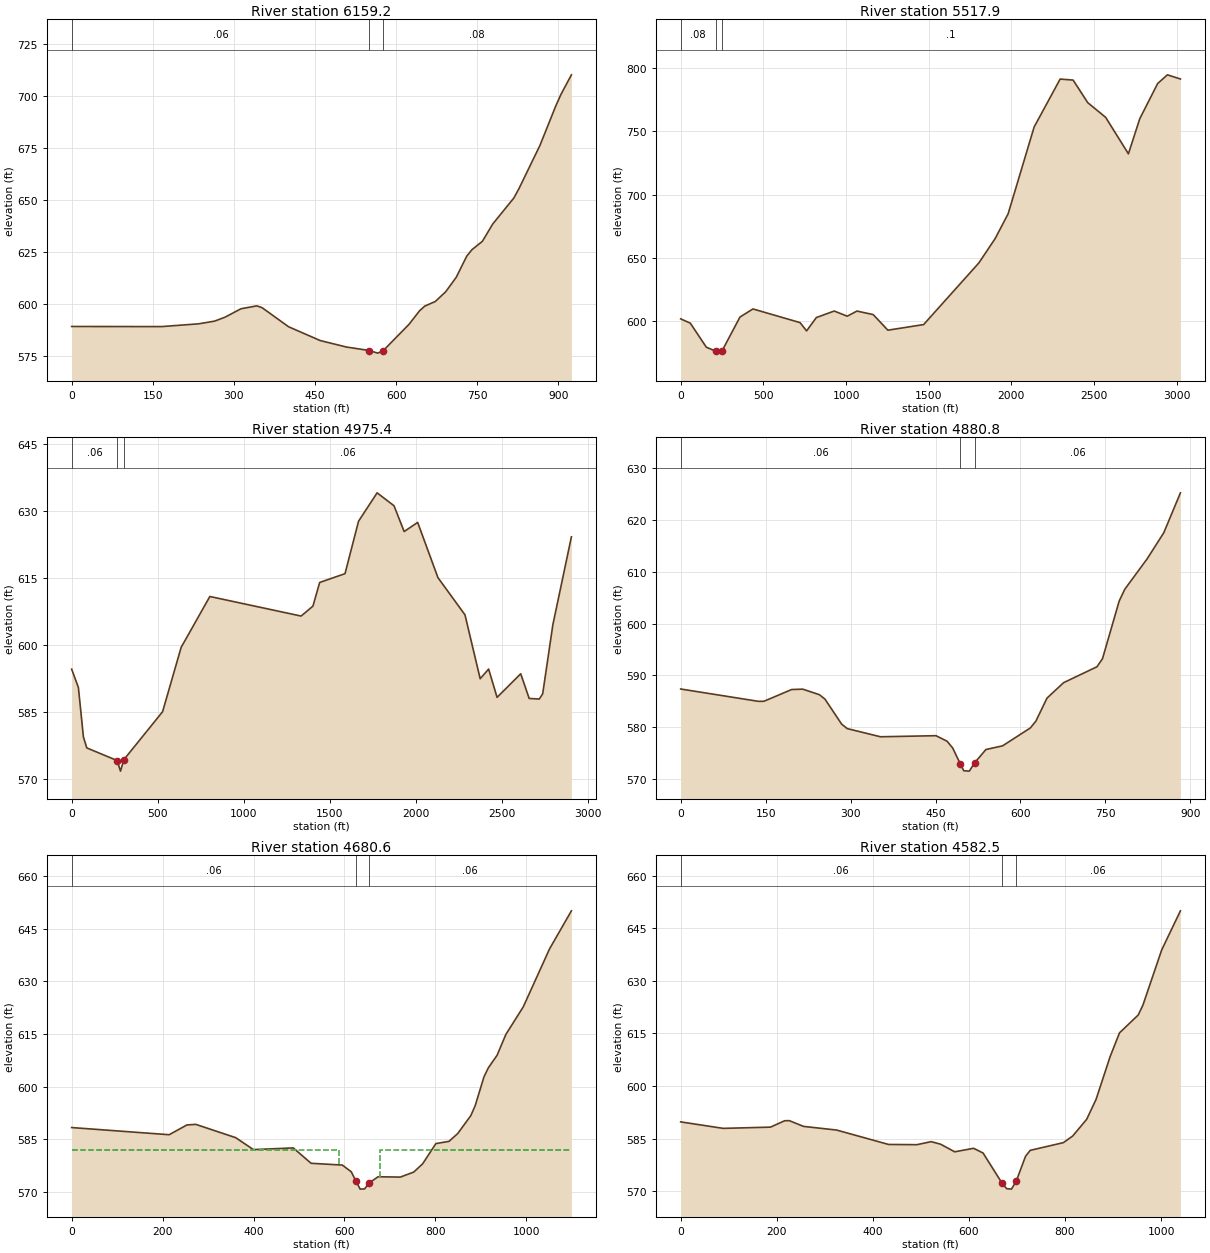
Type RM Length L Ch R = 1 ,6159.2  ,649.8,641.3,633.7
XS GIS Cut Line= 3
     1728233.966      521331.242     1728594.317      521114.188
     1729080.565      520983.968
#Sta/Elev= 30
       0     589   166.3  588.94   234.8  590.28   264.1  591.56   283.7  593.48
   313.1  597.52   342.4  598.92   352.2  598.04   401.1  588.87   459.4  582.25
   507.8  579.13   550.4  577.43   565.9  576.18   575.6  577.23     624  590.09
   643.3  596.54     653  598.81   672.4  601.02   691.7  605.72   711.1  612.64
   730.4  622.76   740.1  625.92   759.5  629.98   778.8  638.36   817.6  650.78
   827.2  655.36     866  676.15     895  694.97   904.7  700.62   924.1  710.06
#Mann= 3 , 0 , 0
       0     .06       0   550.4    .045       0   575.6     .08       0
Bank Sta=550.4,575.6
XS Rating Curve= 0 ,0
Exp/Cntr=0.3,0.1

Type RM Length L Ch R = 1 ,5517.9  ,527.4,542.5,555.6
XS GIS Cut Line= 3
     1728846.091      521708.978     1729158.686      521496.263
     1731677.229      520691.712
#Sta/Elev= 30
       0  601.74    58.2  598.36   155.1  579.36   213.3  576.14   242.4  574.66
   248.4  575.99   358.7   603.2   437.1  609.58   722.1  598.78   761.4  592.23
   820.4  602.77   928.5  607.93  1007.1  603.85  1066.1   607.9  1164.4  605.11
  1252.9  592.79  1469.1  597.23  1803.3  645.97  1901.6  665.19  1980.2  684.79
  2137.4  753.38  2294.7  791.27  2373.3  790.46  2461.8  772.58  2569.9  761.02
  2707.5  732.18  2776.3  759.98  2884.4  787.76  2943.4  794.62    3022  791.32
#Mann= 3 , 0 , 0
       0     .08       0   213.3    .045       0   248.4      .1       0
Bank Sta=213.3,248.4
XS Rating Curve= 0 ,0
Exp/Cntr=0.3,0.1

Type RM Length L Ch R = 1 ,4975.4  ,93.4,94.7,94.4
XS GIS Cut Line= 3
     1728954.616      521943.422     1729532.028      521956.474
     1731859.507      521978.528
#Sta/Elev= 30
       0  594.64    39.2  590.54    68.5  579.44    88.1  577.01   264.3  574.18
   283.9  571.81   303.5  574.38   528.6  585.11   636.5  599.52   803.4  610.91
  1333.8  606.53  1402.5  608.75  1441.8  614.05  1589.1  616.02  1667.7  627.76
  1775.7  634.12  1873.9  631.22  1932.9  625.45  2011.4   627.5  2129.3  615.13
  2286.4  606.81  2374.8   592.5  2423.9  594.66    2473  588.33  2610.5  593.61
  2659.6  588.08  2718.5  587.95  2738.2  589.13  2797.1  604.55  2905.1  624.27
#Mann= 3 , 0 , 0
       0     .06       0   264.3    .045       0   303.5     .06       0
Bank Sta=264.3,303.5
XS Rating Curve= 0 ,0
Exp/Cntr=0.3,0.1

Type RM Length L Ch R = 1 ,4880.8  ,209.9,200.2,191.4
XS GIS Cut Line= 3
     1728763.587      522043.265     1729488.609      522030.277
     1729627.532      522104.088
#Sta/Elev= 30
       0  587.37   137.2  584.99     147     585     196  587.27   215.6  587.34
     245  586.27   254.8  585.42   284.2   580.6     294  579.73   352.8  578.15
   450.8  578.36   470.4  577.29   480.2     576   493.9  572.89   499.8   571.6
   509.6  571.52   519.4  573.18     539  575.69   568.4   576.4   617.4  579.85
   627.2  581.17   646.8  585.61   676.1  588.59     735  591.66   744.8  593.21
   774.3  604.35   784.1  606.61   823.5  612.47     853  617.52   882.4  625.23
#Mann= 3 , 0 , 0
       0     .06       0   493.9    .045       0   519.4     .06       0
Bank Sta=493.9,519.4
XS Rating Curve= 0 ,0
Exp/Cntr=0.3,0.1

Type RM Length L Ch R = 1 ,4680.6  ,99.9,98.1,98.6
XS GIS Cut Line= 4
     1728629.199      522445.168     1729095.308      522245.675
     1729351.848      522147.055     1729668.338      522170.515
#Sta/Elev= 30
       0  588.32   214.5  586.28   253.5  589.06     273  589.23   360.8  585.44
   399.8  582.04   487.5  582.52   526.6  578.14   595.4  577.63     615  575.72
   624.8  573.19   634.6  570.78   644.4  570.85   654.2  572.51   673.9   574.3
     723  574.21   752.4  575.64     772  577.99   801.1  583.75   829.9  584.39
   849.2  586.62     878  591.73   887.6  594.57   906.9  602.77   916.5  605.33
   935.7  608.91     955  614.84   993.4  622.72  1051.1  639.21  1099.2  650.06
#Mann= 3 , 0 , 0
       0     .06       0   624.8    .045       0   654.2     .06       0
#XS Ineff= 2 , 0
       0  588.17     582  677.75       0     582
Permanent Ineff=
       F       F
Bank Sta=624.8,654.2
XS Rating Curve= 0 ,0
Exp/Cntr=0.3,0.1

Type RM Length L Ch R = 1 ,4582.5  ,366.8,385,398.2
XS GIS Cut Line= 4
     1728659.584      522549.364     1729178.616      522312.456
     1729384.622       522219.45     1729628.264       522229.47
#Sta/Elev= 30
       0  589.75    88.5   587.9   186.9  588.25   216.4  590.07   226.2   590.1
   255.8  588.46   324.6  587.42   432.8  583.31   491.8  583.24   521.4  584.11
     541  583.39   570.5  581.21   609.8  582.21   629.5  580.87   668.8  572.32
   678.6   570.7   688.5  570.56   698.3  572.74     718  579.95   727.8  581.63
   796.6  583.82   816.1  585.71   845.3   590.5   864.8  596.18   894.1   608.4
   913.6  615.16   952.6  620.26   962.4   623.1  1001.4  638.82  1040.4  649.98
#Mann= 3 , 0 , 0
       0     .06       0   668.8    .045       0   698.3     .06       0
Bank Sta=668.8,698.3
XS Rating Curve= 0 ,0
Exp/Cntr=0.3,0.1

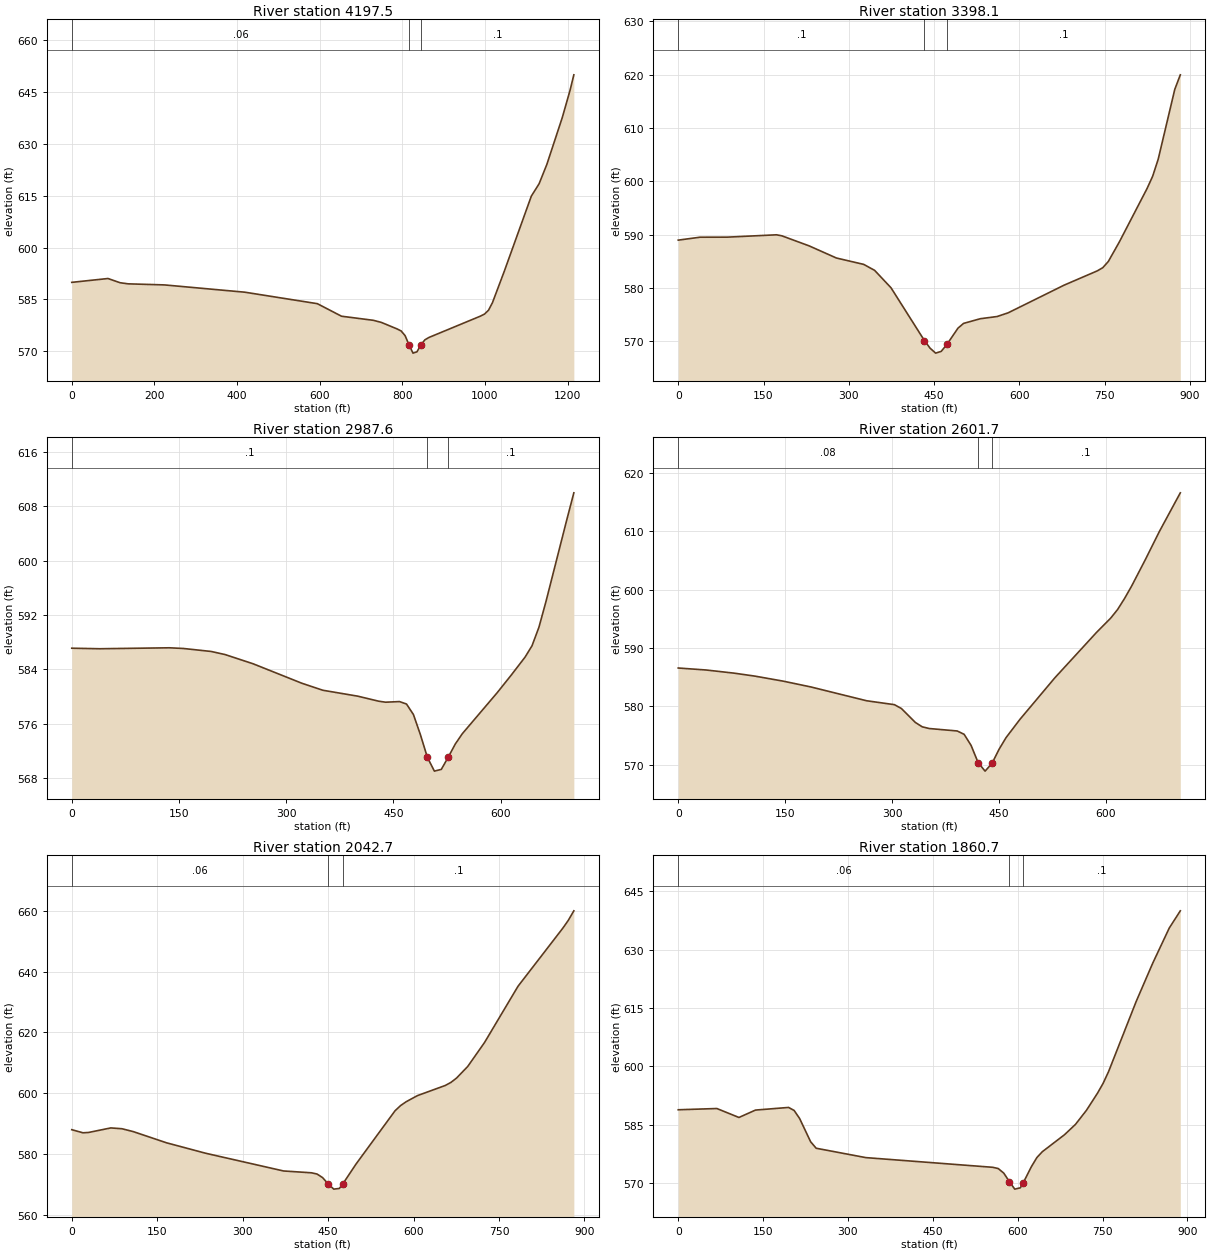
Type RM Length L Ch R = 1 ,4197.5  ,816.1,799.4,781.2
XS GIS Cut Line= 4
      1728487.27      522760.537      1729102.78      522542.777
      1729481.32      522611.416     1729657.614       522588.88
#Sta/Elev= 30
       0  589.95    87.7  591.06   116.9  589.84   136.4  589.52   224.1  589.21
     419   587.1   594.4  583.78   652.9  580.15   729.8  578.97   749.1  578.37
   787.5  576.47   797.2  575.89   806.8  574.54   816.4  571.84     826  569.47
   835.6  569.85   845.2   571.9   854.9  573.33   864.5     574   989.5  580.19
   999.1  580.77  1008.8  581.89  1018.4   584.1    1047  593.18  1112.4   614.9
  1131.2  618.48  1149.9  624.06  1187.3  637.63    1206  645.47  1215.3     650
#Mann= 3 , 0 , 0
       0     .06       0   816.4    .045       0   845.2      .1       0
Bank Sta=816.4,845.2
XS Rating Curve= 0 ,0
Exp/Cntr=0.3,0.1

Type RM Length L Ch R = 1 ,3398.1  ,400.7,410.5,419.8
XS GIS Cut Line= 4
     1728834.969      523311.537       1729196.9      523216.916
      1729436.72      523045.994     1729647.143       523005.81
#Sta/Elev= 30
       0  588.95    38.4   589.5    86.3  589.51   172.7  589.95   182.2  589.76
   230.2  587.87   278.2  585.59   326.1   584.4   345.3  583.28   374.1  580.01
     433  570.08   442.8  568.67   452.6  567.74   462.4  568.07   472.6   569.4
   491.9  572.43   501.7  573.32   531.2   574.2   560.6  574.61   580.2  575.31
   678.3  580.49   736.8  583.18   746.5  583.78   756.2  584.94   775.7  588.63
   824.4  598.65   834.1  600.92   843.9  604.13   873.1  617.26   882.8  619.98
#Mann= 3 , 0 , 0
       0      .1       0     433    .045       0   472.6      .1       0
Bank Sta=433,472.6
XS Rating Curve= 0 ,0
Exp/Cntr=0.3,0.1

Type RM Length L Ch R = 1 ,2987.6  ,385.8,385.9,385.2
XS GIS Cut Line= 2
     1729028.558      523526.209      1729712.67      523367.023
#Sta/Elev= 30
       0   587.1      39  587.02   136.6  587.16   156.1  587.06   195.1  586.62
   214.6  586.16   253.6  584.81   321.9  581.94   351.2  580.91     400  580.04
   429.2   579.3     439  579.15   458.5  579.24   468.3  578.88     478  577.33
   487.8  574.35   497.5  571.03   507.3     569     517  569.26   526.8  571.08
   536.6     573   546.3   574.5   595.1  580.54   614.6  583.11   634.1  585.78
   643.9  587.46   653.6   590.2   663.4  593.97   692.6  606.04   702.4  609.98
#Mann= 3 , 0 , 0
       0      .1       0   497.5    .045       0   526.8      .1       0
Bank Sta=497.5,526.8
XS Rating Curve= 0 ,0
Exp/Cntr=0.3,0.1

Type RM Length L Ch R = 1 ,2601.7  ,559.8,559,557.7
XS GIS Cut Line= 2
     1729146.022      523874.009     1729830.081       523705.75
#Sta/Elev= 30
       0  586.56    39.1  586.22    78.3  585.68   107.6  585.17   146.8  584.32
   185.9  583.32   264.2  580.95   303.3  580.28   313.1  579.62   332.7  577.23
   342.4  576.48   352.2  576.19   391.4  575.77   401.1   575.2   410.9  573.29
   420.7  570.36   430.5  568.89   440.3  570.23   450.1  572.63   459.8  574.61
   479.4  577.76   528.3  584.87     587  592.68   606.6  595.09   616.4  596.58
   626.2  598.48     636  600.58   655.5  605.17   675.1  609.97   704.4  616.58
#Mann= 3 , 0 , 0
       0     .08       0   420.7    .045       0   440.3      .1       0
Bank Sta=420.7,440.3
XS Rating Curve= 0 ,0
Exp/Cntr=0.3,0.1

Type RM Length L Ch R = 1 ,2042.7  ,187.7,182,176.2
XS GIS Cut Line= 3
     1729267.292      524424.901     1729781.448      524266.007
     1730093.048      524121.945
#Sta/Elev= 30
       0  588.02    19.6     587    29.4   587.1    68.5   588.6    88.1  588.33
   107.6  587.41   166.3  583.71   234.8  580.28   371.8  574.44   420.7  573.84
   430.5  573.44   440.3  572.26   450.1  570.19   459.9  568.47   469.7  568.69
   475.6  570.12     499  576.71   567.6  594.26   577.4  595.97   587.2  597.23
   606.8  599.22   655.8  602.57   665.7  603.58   675.5     605   695.1  608.81
   724.5  616.66   783.4  635.19   861.8  654.23   871.6  656.85   881.4     660
#Mann= 3 , 0 , 0
       0     .06       0   450.1    .045       0   475.6      .1       0
Bank Sta=450.1,475.6
XS Rating Curve= 0 ,0
Exp/Cntr=0.3,0.1

Type RM Length L Ch R = 1 ,1860.7  ,575.2,572.4,569.6
XS GIS Cut Line= 2
     1729295.715      524733.862     1730066.409      524293.925
#Sta/Elev= 30
       0  588.86    68.3  589.18   107.3  586.88   136.5  588.78     195  589.46
   204.8  588.69   214.5  586.63     234  580.64   243.8  578.97   331.6  576.56
   555.9  574.07   565.6  573.75   575.4  572.57   585.1  570.42   594.8  568.46
   604.6  568.79   609.8  570.09   624.1  574.21   633.9  576.58   643.6  578.09
   682.6  582.43   702.1   585.1   721.6  588.74   741.1  593.14   750.9  595.64
   760.6  598.67   809.4   616.7   838.7  626.56   867.9  635.58   887.4     640
#Mann= 3 , 0 , 0
       0     .06       0   585.1    .045       0   609.8      .1       0
Bank Sta=585.1,609.8
XS Rating Curve= 0 ,0
Exp/Cntr=0.3,0.1

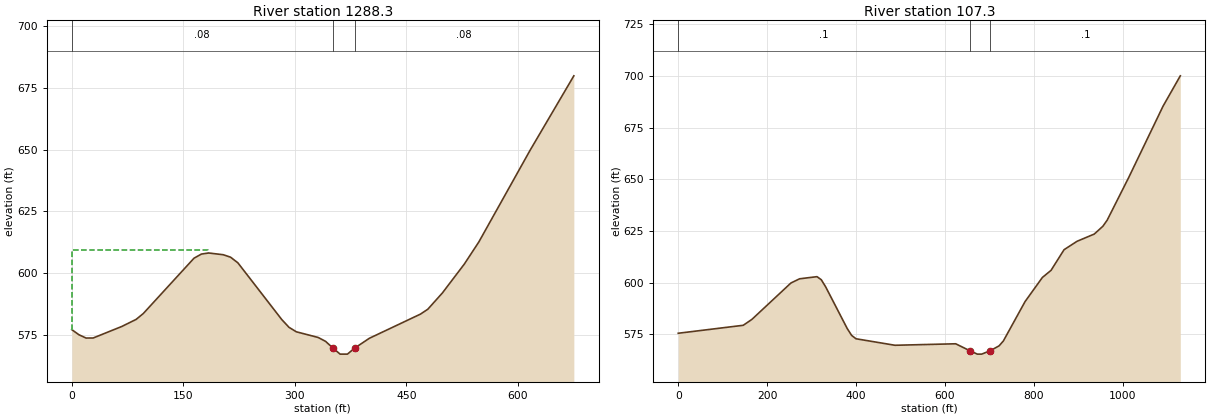
Type RM Length L Ch R = 1 ,1288.3  ,1179.9,1181,1182.1
XS GIS Cut Line= 3
     1729870.278      525082.953     1729973.891      525032.112
     1730422.176      524696.607
#Sta/Elev= 30
       0  577.12     9.6  575.04    19.2   573.7    28.8  573.72    67.3  578.39
    86.6  581.26    96.2  583.63   164.5  606.08   174.4  607.74   184.2  608.18
   203.8  607.47   213.6  606.48   223.5  604.18   282.4  581.23   292.2  578.05
   302.1  576.23   331.5  573.93   341.4  572.36   351.2  569.69     361  567.18
   370.8  567.18   380.6  569.62   400.3   573.6     469  583.39   478.9  585.36
   498.5  591.95     528  603.66   547.6  612.65   616.4  649.74   675.4     680
#Mann= 3 , 0 , 0
       0     .08       0   351.2    .045       0   380.6     .08       0
#XS Ineff= 2 , 0
          183.38  609.34
Permanent Ineff=
       F       F
Bank Sta=351.2,380.6
XS Rating Curve= 0 ,0
Exp/Cntr=0.3,0.1

Type RM Length L Ch R = 1 ,107.3   ,108.1,107.3,106.4
XS GIS Cut Line= 3
     1730344.461      526188.019     1731088.236      525685.807
     1731320.463      525679.958
#Sta/Elev= 30
       0  575.54   146.3  579.39   165.8  582.25   253.6  599.84   273.1  601.87
   312.2   602.9   321.9  601.42   331.7     598   380.4  577.77   390.2   574.5
     400  572.88   487.8  569.73   624.3  570.45   657.1     567   673.1  565.45
   682.8  565.45   702.4  567.13   721.9  569.44   731.6   571.8   780.4  590.83
   819.4  602.51   838.9  605.95   868.2  615.93   897.4     620   936.2   623.5
   955.5  627.26   965.2   630.2  1013.6   650.8    1091  685.34  1129.8     700
#Mann= 3 , 0 , 0
       0      .1       0   657.1    .045       0   702.4      .1       0
Bank Sta=657.1,702.4
XS Rating Curve= 0 ,0
Exp/Cntr=0.3,0.1

Chan Stop Cuts=-1
Use User Specified Reach Order=0
Composite Channel Slope=5